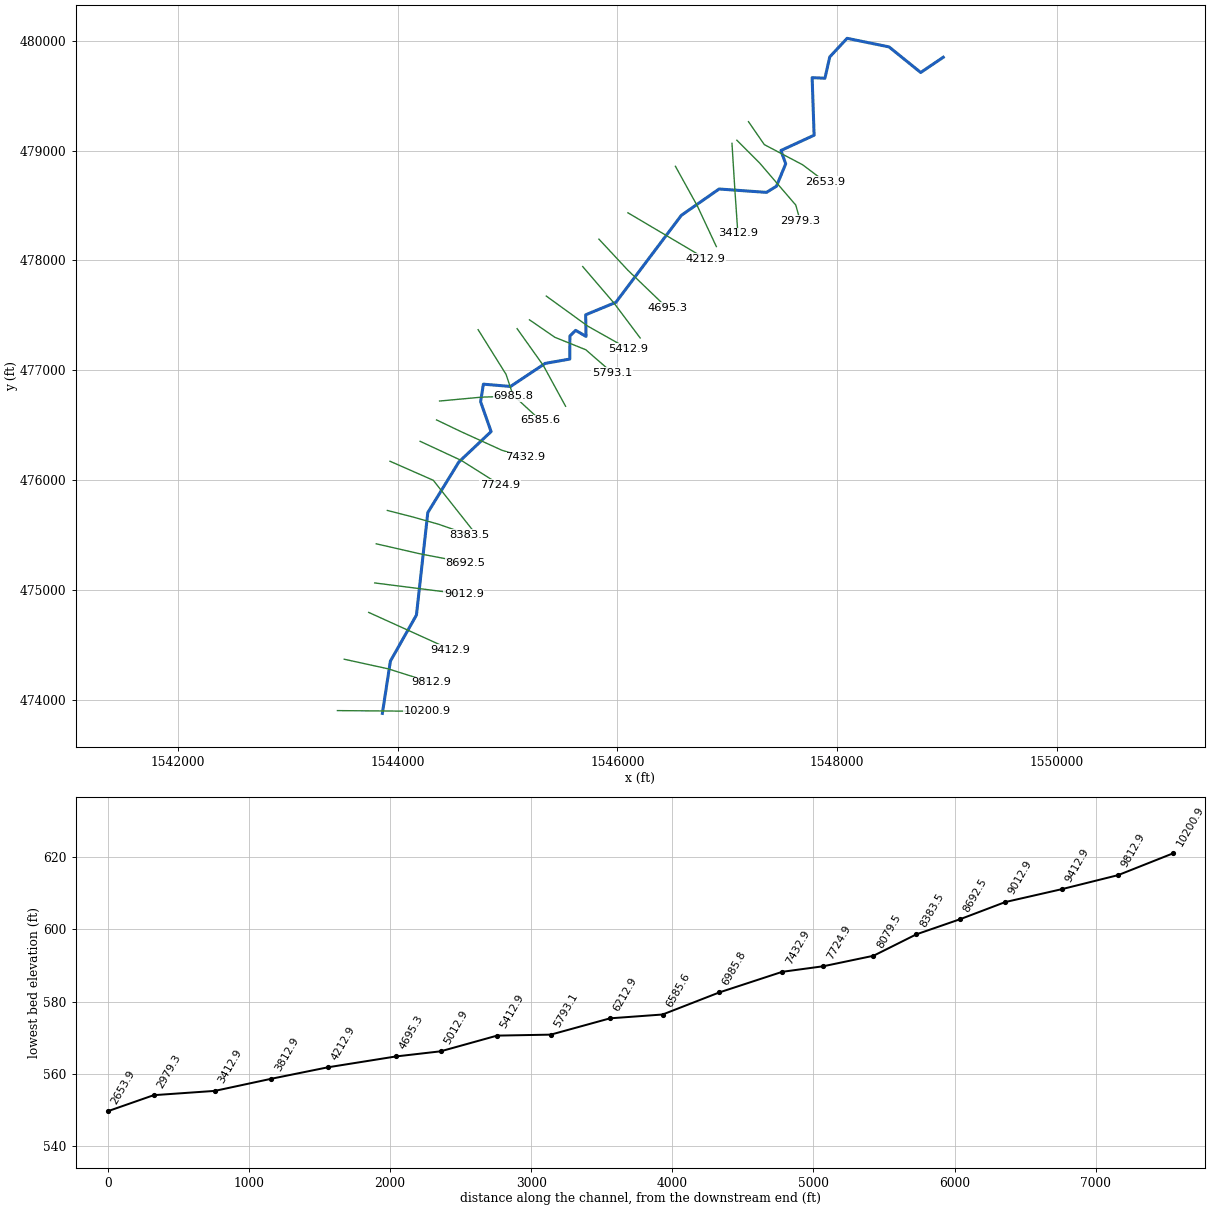
--- LYNNCR.prj (project) ---

Proj Title=LYNNCR
Current Plan=p01
Default Exp/Contr=0,0
English Units
Geom File=g01
Flow File=f01
Plan File=p01
BEGIN DESCRIPTION:
END DESCRIPTION:
DSS Export Rating Curves= 0
DSS Export Rating Curve Sorted= 0
DSS Export Volume Flow Curves= 0
DXF OffsetX= 0
DXF OffsetY= 0
DXF ScaleX= 0
DXF ScaleY= 0

--- LYNNCR.p01 (plan) ---

Plan Title=Floodplain
Program Version=4.00
Geom File=g01
Flow File=f01
K Sum by GR=0
Std Step Tol=0.01
Critical Tol=0.01
Num of Std Step Trials=20
Max Error Tol=0.3
Flow Tol Ratio=0.001
Split Flow NTrial=30
Split Flow Tol=0.02
Split Flow Ratio=0.02
Log Output Level=0
Friction Slope Method=1
Unsteady Friction Slope Method=2
Unsteady Bridges Friction Slope Method=1
Global Log Level=0
CheckData=False
Run HTab=0
Run UNet=0
Run PostProcess=0
UNET Theta=0
UNET Theta Warmup=0
UNET ZTol=0
UNET ZSATol=0
UNET MxIter=0
UNET MaxInSteps=0
UNET DtIC=0
UNET DtMin=0
UNET MaxCRTS=0
UNET WFStab=0
UNET SFStab=0
UNET WFX=0
UNET SFX=0
UNET DSS MLevel=0
UNET DZMax Abort=0
UNET Convert EG Bridges=0
UNET Use Existing IB Tables=0
UNET Froude Limit=0
UNET Froude Power=0
Write IC File=0
Echo Input=False
Echo Output=False
Write Detailed=0

--- LYNNCR.f01 (steady flow) ---

Flow Title=NFF Regression Equation
Program Version=4.00
Number of Profiles=1
Profile Names=P100yr
River Rch & RM=LYNNCR,Main      ,10200.9
     420
River Rch & RM=LYNNCR,Main      ,8383.5
     450
River Rch & RM=LYNNCR,Main      ,8079.5
     591
River Rch & RM=LYNNCR,Main      ,6585.6
     642
River Rch & RM=LYNNCR,Main      ,2979.3
     711
River Rch & RM=LYNNCR,Main      ,2653.9
     860
Boundary for River Rch & Prof#=LYNNCR,Main      ,1
Up Type=0
Dn Type=3
Dn Slope=0.00828

--- LYNNCR.g01 (geometry) ---

Geom Title=USGS 10m DEM
Program Version=4.00

River Reach=LYNNCR          ,Main
Reach XY= 30
     1543860.194      473877.331     1543933.122      474352.446
     1544170.539      474772.187     1544273.952      475704.963
     1544556.841      476165.315     1544850.414      476442.216
     1544754.719      476714.026     1544780.211       476873.58
     1545027.513       476852.79     1545342.715      477062.621
     1545567.305      477102.213     1545568.096      477312.286
     1545620.531      477363.287     1545715.205      477308.299
     1545711.548       477504.95      1545986.91      477618.407
     1546583.105      478410.271      1546926.99      478650.008
     1547358.762      478619.294     1547449.421      478675.372
     1547533.714      478879.361     1547490.023      479000.389
     1547792.321      479139.386      1547774.39      479663.205
     1547890.923      479658.248     1547934.931      479852.313
     1548092.794      480021.256     1548474.636      479943.483
     1548763.203      479710.402     1548968.254      479848.872

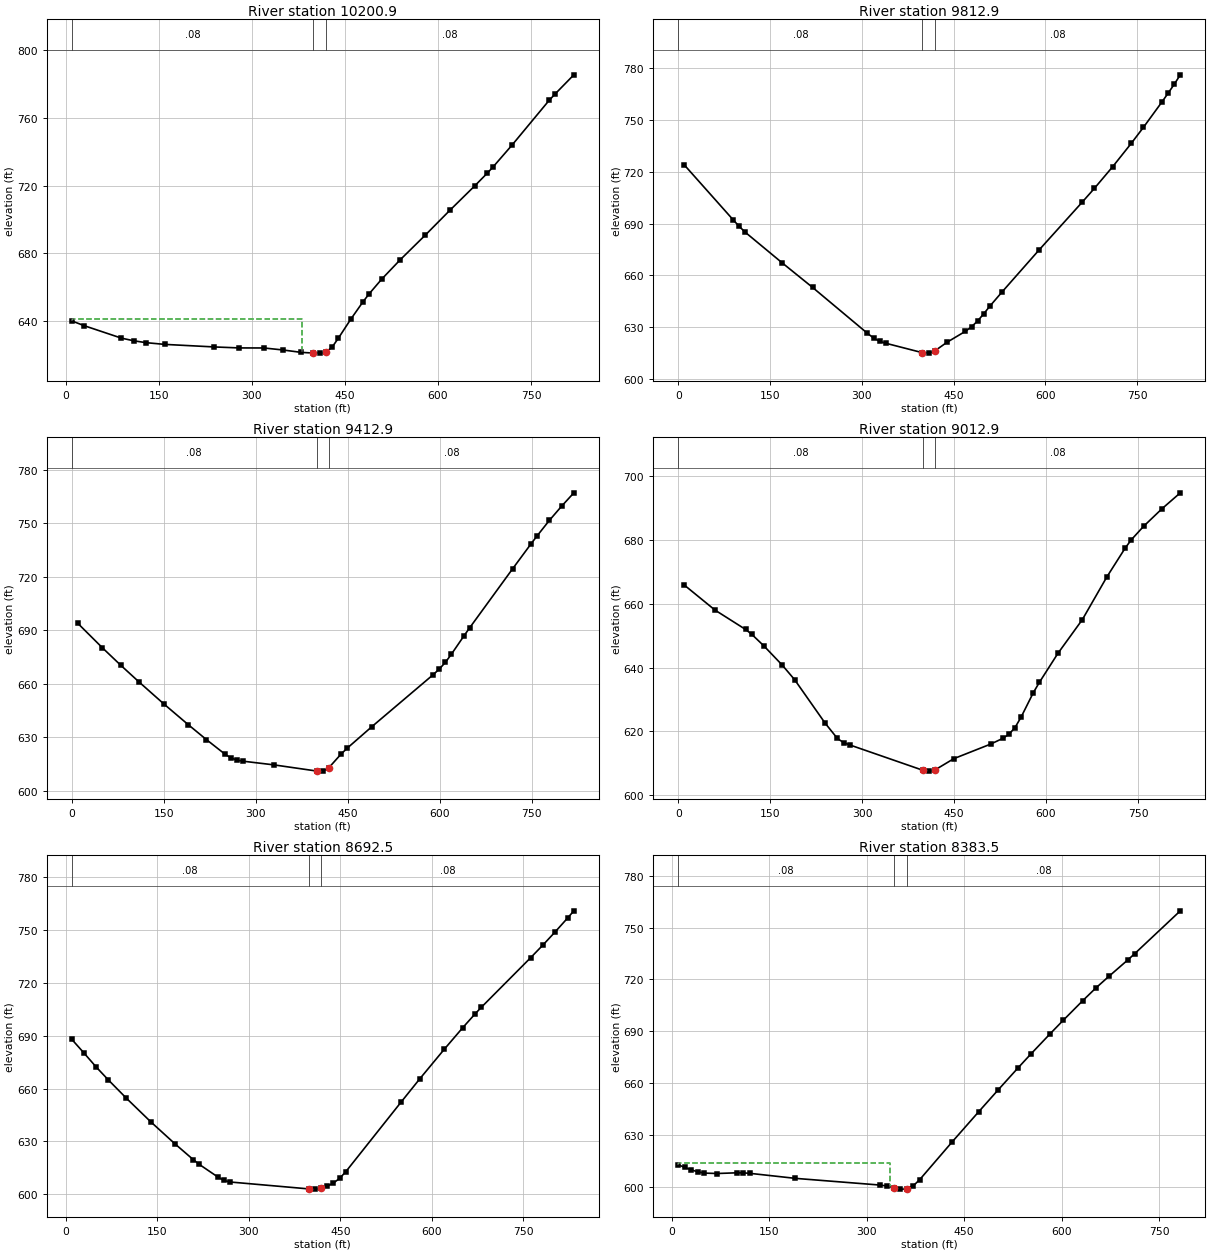
Type RM Length L Ch R = 1 ,10200.9 ,393.2,388.1,380.6
XS GIS Cut Line= 3
     1543450.791      473902.682     1543860.277      473899.272
     1544269.763      473895.863
#Sta/Elev= 30
      10   640.1      30  637.27    89.9  629.93   109.9  628.35   129.8  627.24
   159.8  626.23   239.7  624.72   279.7  624.14   319.6  624.11   349.6  622.96
   379.5  621.52   399.5  621.11   409.5  621.07   419.5  621.64   429.5  624.62
   439.5  629.85   459.4     641   479.4  651.44   489.4  656.18   509.4  664.74
   539.3   676.2   579.3  690.61   619.2  705.37   659.2  719.76   679.2  727.18
   689.2  731.13   719.1  743.74     779   770.2     789  774.13     819  785.35
#Mann= 3 , 0 , 0
      10     .08       0   399.5    .045       0   419.5     .08       0
#XS Ineff= 2 , 0
          380.97   641.2
Permanent Ineff=
       F       F
Bank Sta=399.5,419.5
XS Rating Curve= 0 ,0
Exp/Cntr=0.3,0.1

Type RM Length L Ch R = 1 ,9812.9  ,405.3,400,397
XS GIS Cut Line= 3
     1543512.808      474370.167     1543912.526      474282.882
     1544304.986      474158.963
#Sta/Elev= 30
      10  723.95    89.8   692.2    99.8  688.35   109.8  684.94   169.6  667.39
   219.5  653.11   309.3  626.51   319.3   623.8   329.3  621.87   339.3  620.76
   399.1  615.31   409.1  615.05   419.1  616.26   439.3  621.33   469.4  627.68
   479.4   630.3   489.4  633.68   499.5  637.88   509.5  642.29   529.6  650.57
   589.8  674.75   660.1  702.34   680.2   710.4   710.3  723.02   740.4  736.42
   760.5  745.78   790.6   760.4   800.6  765.43   810.7  770.64   820.7  776.14
#Mann= 3 , 0 , 0
       0     .08       0   399.1    .045       0   419.1     .08       0
Bank Sta=399.1,419.1
XS Rating Curve= 0 ,0
Exp/Cntr=0.3,0.1

Type RM Length L Ch R = 1 ,9412.9  ,392.4,400,407.6
XS GIS Cut Line= 3
     1543735.532       474796.47     1544108.478      474627.351
     1544481.424      474458.232
#Sta/Elev= 30
      10  693.85    49.9  680.23    79.9  670.43   109.9  661.02   149.8  648.89
   189.8  637.22   219.7  628.79   249.7   620.7   259.7  618.53   269.7  617.28
   279.7   616.7   329.6  614.66   399.5   611.2   409.5  611.15   419.5  613.11
   439.5  620.78   449.5  624.06   489.4  636.01   589.3  665.08   599.3  668.24
   609.3  671.99   619.2  676.58   639.2  686.61   649.2  691.46   719.1  724.43
   749.1  738.38   759.1  742.89     779  751.51     799  759.47     819  766.97
#Mann= 3 , 0 , 0
       0     .08       0   399.5    .045       0   419.5     .08       0
Bank Sta=399.5,419.5
XS Rating Curve= 0 ,0
Exp/Cntr=0.3,0.1

Type RM Length L Ch R = 1 ,9012.9  ,323.5,320.4,318.2
XS GIS Cut Line= 3
     1543790.303       475064.52     1544196.559      475013.078
     1544602.815      474961.635
#Sta/Elev= 30
      10  665.83    59.9  658.02   109.9  651.94   119.9  650.43   139.8  646.78
   169.8  640.75   189.8  636.23   239.7  622.58   259.7   617.8   269.7  616.51
   279.7  615.79   399.5  607.82   409.5  607.58   419.5  608.03   449.5  611.48
   509.4  616.03   529.4  617.83   539.3   619.1   549.3  621.21   559.3   624.5
   579.3  632.18   589.3  635.44   619.2  644.42   659.2  655.03   699.1  668.37
   729.1  677.44   739.1  680.04   759.1  684.24     789  689.73     819  694.73
#Mann= 3 , 0 , 0
       0     .08       0   399.5    .045       0   419.5     .08       0
Bank Sta=399.5,419.5
XS Rating Curve= 0 ,0
Exp/Cntr=0.3,0.1

Type RM Length L Ch R = 1 ,8692.5  ,309.6,309,307.4
XS GIS Cut Line= 3
     1543804.403       475420.68     1544202.642      475329.664
     1544619.294      475249.685
#Sta/Elev= 30
      10  687.96    29.9  680.22    49.8   672.3    69.7  664.97    99.6  654.45
   139.5  641.06   179.3   628.5   209.2  619.56   219.2  616.82   249.1  609.78
   259.1  607.78     269  606.89   398.5  602.94   409.1  602.82   418.5  603.38
   428.7  604.54   438.8  606.29   448.9  608.92     459  612.69   549.9  652.38
   580.2  665.46   620.6  682.37   650.9  694.65   671.1  702.47   681.2  706.17
   762.1  734.38   782.3  741.61   802.5  749.14   822.7  756.95   832.8  760.99
#Mann= 3 , 0 , 0
      10     .08       0   398.5    .045       0   418.5     .08       0
Bank Sta=398.5,418.5
XS Rating Curve= 0 ,0
Exp/Cntr=0.3,0.1

Type RM Length L Ch R = 1 ,8383.5  ,319.9,304,288.2
XS GIS Cut Line= 4
     1543905.801      475724.352     1544138.657      475664.645
     1544371.512      475598.968     1544655.118      475500.452
#Sta/Elev= 30
      10  612.76      20  611.17      30  609.81    40.1  608.64    50.1  607.92
    70.1  607.68   100.2  608.09   110.2  608.05   120.2  607.78   190.3  604.87
     321  600.98   331.1  600.45   341.3  599.53   351.3  598.64   361.3  598.68
   371.4  600.47   381.5   604.1   431.9  626.14   472.2  643.36   502.3  656.08
   532.4  668.61   552.4  676.74   582.4   688.6   602.4  696.34   632.4  707.69
   652.5     715   672.5  721.72   702.5  731.52   712.5  734.94   782.6  759.71
#Mann= 3 , 0 , 0
      10     .08       0   341.3    .045       0   361.3     .08       0
#XS Ineff= 2 , 0
          336.14  613.98
Permanent Ineff=
       F       F
Bank Sta=341.3,361.3
XS Rating Curve= 0 ,0
Exp/Cntr=0.3,0.1

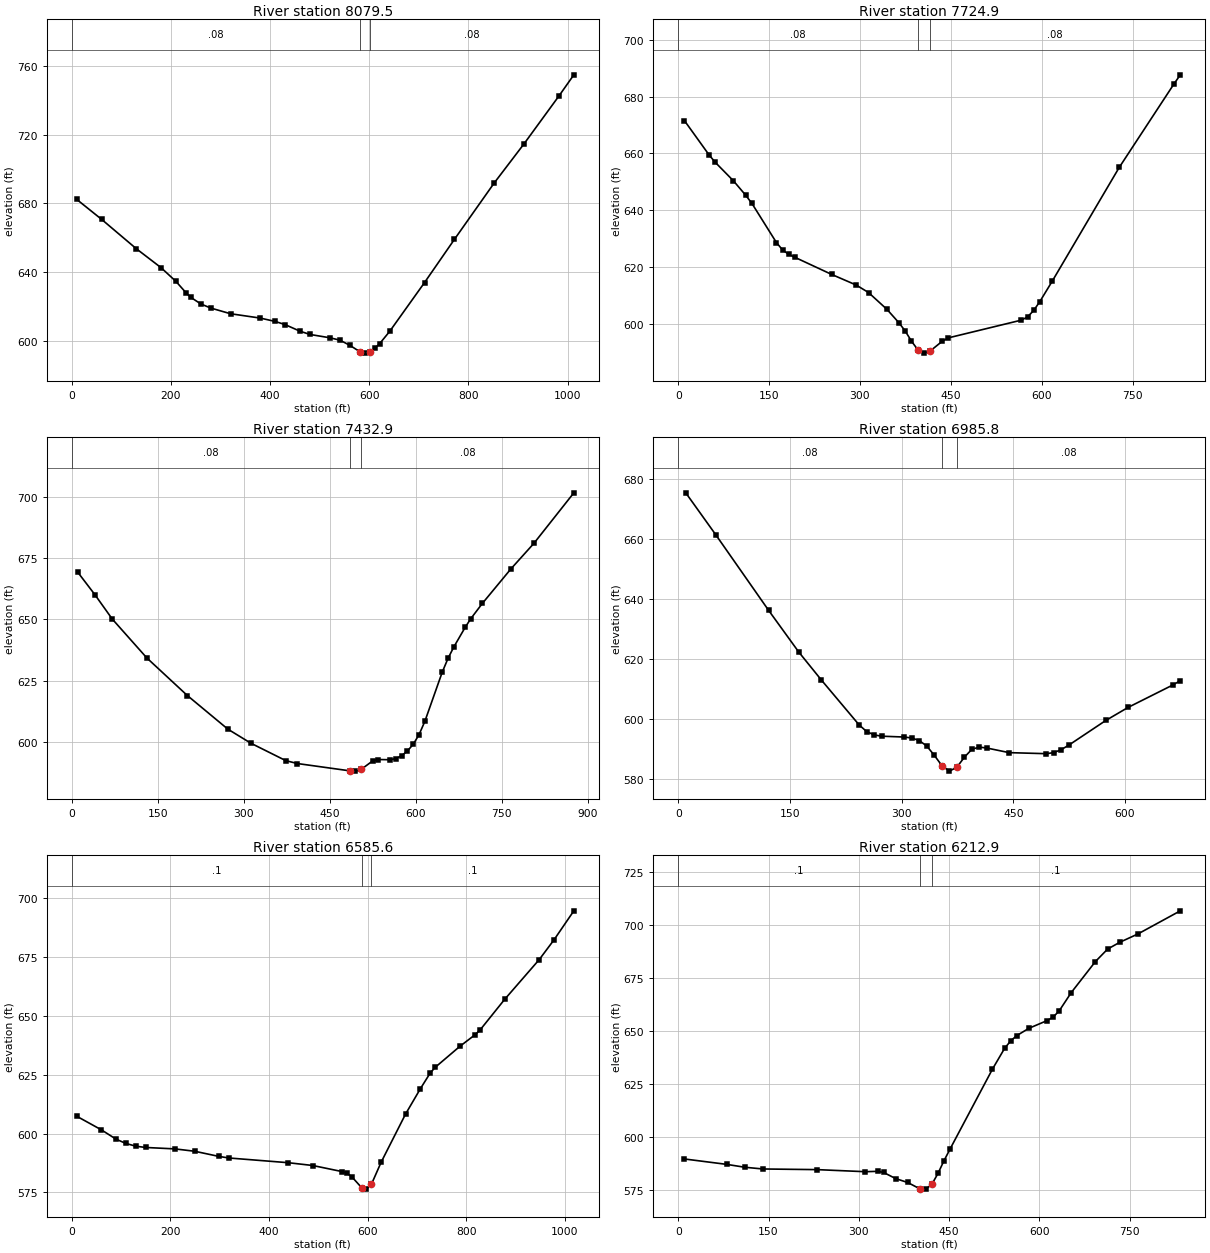
Type RM Length L Ch R = 1 ,8079.5  ,342.8,354.6,364.5
XS GIS Cut Line= 3
     1543929.684       476172.15     1544323.747      475999.001
     1544684.971      475542.247
#Sta/Elev= 30
      10  682.23    60.1  670.63   130.1  653.53   180.2  642.45   210.2  634.45
   230.2  627.95   240.2  625.17   260.3  621.35   280.3  618.96   320.3  615.64
   380.4   613.1   410.4  611.15   430.4   609.3   460.5  605.46   480.6  603.57
   520.8  601.63   540.9  600.26   560.9  597.25   581.1  593.54   591.1   592.7
   601.1  593.35   611.1  595.41   621.2  598.28   641.3  605.36   711.6   633.8
   771.8  658.92   852.1  691.78   912.4  714.62   982.6  742.41  1012.8  754.78
#Mann= 3 , 0 , 0
       0     .08       0   581.1    .045       0   601.1     .08       0
Bank Sta=581.1,601.1
XS Rating Curve= 0 ,0
Exp/Cntr=0.3,0.1

Type RM Length L Ch R = 1 ,7724.9  ,292,292.1,293.9
XS GIS Cut Line= 3
     1544204.452      476353.469     1544581.159      476178.421
     1544930.784      475957.821
#Sta/Elev= 30
    10.1  671.56    50.7  659.53    60.8  656.93    91.2  650.34   111.4  645.29
   121.6  642.43   162.1  628.66   172.2  626.08   182.4  624.52   192.5  623.48
   253.3  617.46   293.8  613.73   314.1   611.1   344.5  605.19   364.7  600.38
   374.9   597.5     385  594.01   395.3  591.04   405.3   589.8   415.3  590.44
   435.6  593.94   445.6  595.15   566.6  601.41   576.7  602.53   586.8  604.81
   596.9  607.91   617.1  614.99     728  655.09   818.7  684.54   828.8  687.62
#Mann= 3 , 0 , 0
       0     .08       0   395.3    .045       0   415.3     .08       0
Bank Sta=395.3,415.3
XS Rating Curve= 0 ,0
Exp/Cntr=0.3,0.1

Type RM Length L Ch R = 1 ,7432.9  ,434.2,447.1,459.4
XS GIS Cut Line= 4
     1544353.634      476548.429     1544571.761      476443.778
     1544949.053      476272.179     1545159.038      476208.256
#Sta/Elev= 30
    10.1   669.3    40.3  660.07    70.6  650.15     131   634.3   201.6  619.02
   272.3  605.33   312.7  599.58   373.4  592.52   393.6  591.34   484.7  588.38
   494.7  588.25   504.7  588.93     525  592.42   535.1  592.97   555.3  592.89
   565.4  593.35   575.5  594.54   585.6  596.46   595.8   599.2   605.9  603.13
     616  608.52   646.3  628.53   656.4  634.14   666.4  638.73   686.3  646.76
   696.3  650.35   716.3   656.5   766.2  670.57   806.1  680.91   875.9   701.5
#Mann= 3 , 0 , 0
       0     .08       0   484.7    .045       0   504.7     .08       0
Bank Sta=484.7,504.7
XS Rating Curve= 0 ,0
Exp/Cntr=0.3,0.1

Type RM Length L Ch R = 1 ,6985.8  ,432.8,400.2,368.2
XS GIS Cut Line= 3
     1544381.132      476720.138     1544764.042      476755.573
     1545053.772      476764.541
#Sta/Elev= 30
    10.1  675.25    50.6  661.21   121.4  636.09   161.9   622.2   192.3  612.87
   242.9  597.94     253  595.72   263.1  594.59   273.2  594.16   303.6  593.88
   313.7  593.56   323.8   592.7   333.9  590.86   344.1  587.75   354.3   584.3
   364.3  582.52   374.3  583.83   384.5   587.2   394.5  589.81   404.5  590.52
   414.5  590.22   444.5  588.68   494.5  588.33   504.5  588.69   514.5  589.69
   524.5  591.16   574.5  599.43   604.4  603.77   664.4  611.23   674.4  612.66
#Mann= 3 , 0 , 0
       0     .08       0   354.3    .045       0   374.3     .08       0
Bank Sta=354.3,374.3
XS Rating Curve= 0 ,0
Exp/Cntr=0.3,0.1

Type RM Length L Ch R = 1 ,6585.6  ,364.5,372.7,377.7
XS GIS Cut Line= 4
     1544732.736      477369.266     1544986.489      476963.262
     1545049.181      476775.186     1545300.258      476544.132
#Sta/Elev= 30
      10  607.34    59.8   601.6    89.8  597.61   109.7   595.8   129.7  594.64
   149.6  594.09   209.5  593.48   249.4  592.48   299.2  590.26   319.2  589.62
   438.9  587.63   488.7  586.44   548.2  583.86   558.1  583.16     568  581.64
   587.7  577.08   597.7  576.42   607.7  578.48   627.5  587.88     677  608.29
   707.1  619.05   727.2  625.76   737.2  628.11   787.4  637.04   817.5  641.83
   827.6  643.81   877.7  656.86     948  673.78   978.1  682.19  1018.2  694.46
#Mann= 3 , 0 , 0
       0      .1       0   587.7    .045       0   607.7      .1       0
Bank Sta=587.7,607.7
XS Rating Curve= 0 ,0
Exp/Cntr=0.3,0.1

Type RM Length L Ch R = 1 ,6212.9  ,405.3,419.7,437.3
XS GIS Cut Line= 3
     1545087.241      477378.745     1545326.118      477043.749
     1545528.747       476672.62
#Sta/Elev= 30
      10   589.6    80.3  587.05   110.4  585.69   140.5  584.87   230.8  584.56
   311.1  583.58   331.2  583.76   341.2  583.24   361.3  580.33   381.3  578.49
   401.4  575.52   411.4  575.36   421.4   577.6   431.6  582.77   441.6  588.76
   451.7  594.29   522.2  632.01   542.3  641.77   552.4   645.3   562.5  647.79
   582.6  651.23   612.8  654.86   622.9  656.52   632.9  659.41   653.1  668.11
   693.3  682.76   713.5  688.62   733.6  691.81   763.8  695.75   834.3  706.67
#Mann= 3 , 0 , 0
       0      .1       0   401.4    .045       0   421.4      .1       0
Bank Sta=401.4,421.4
XS Rating Curve= 0 ,0
Exp/Cntr=0.3,0.1

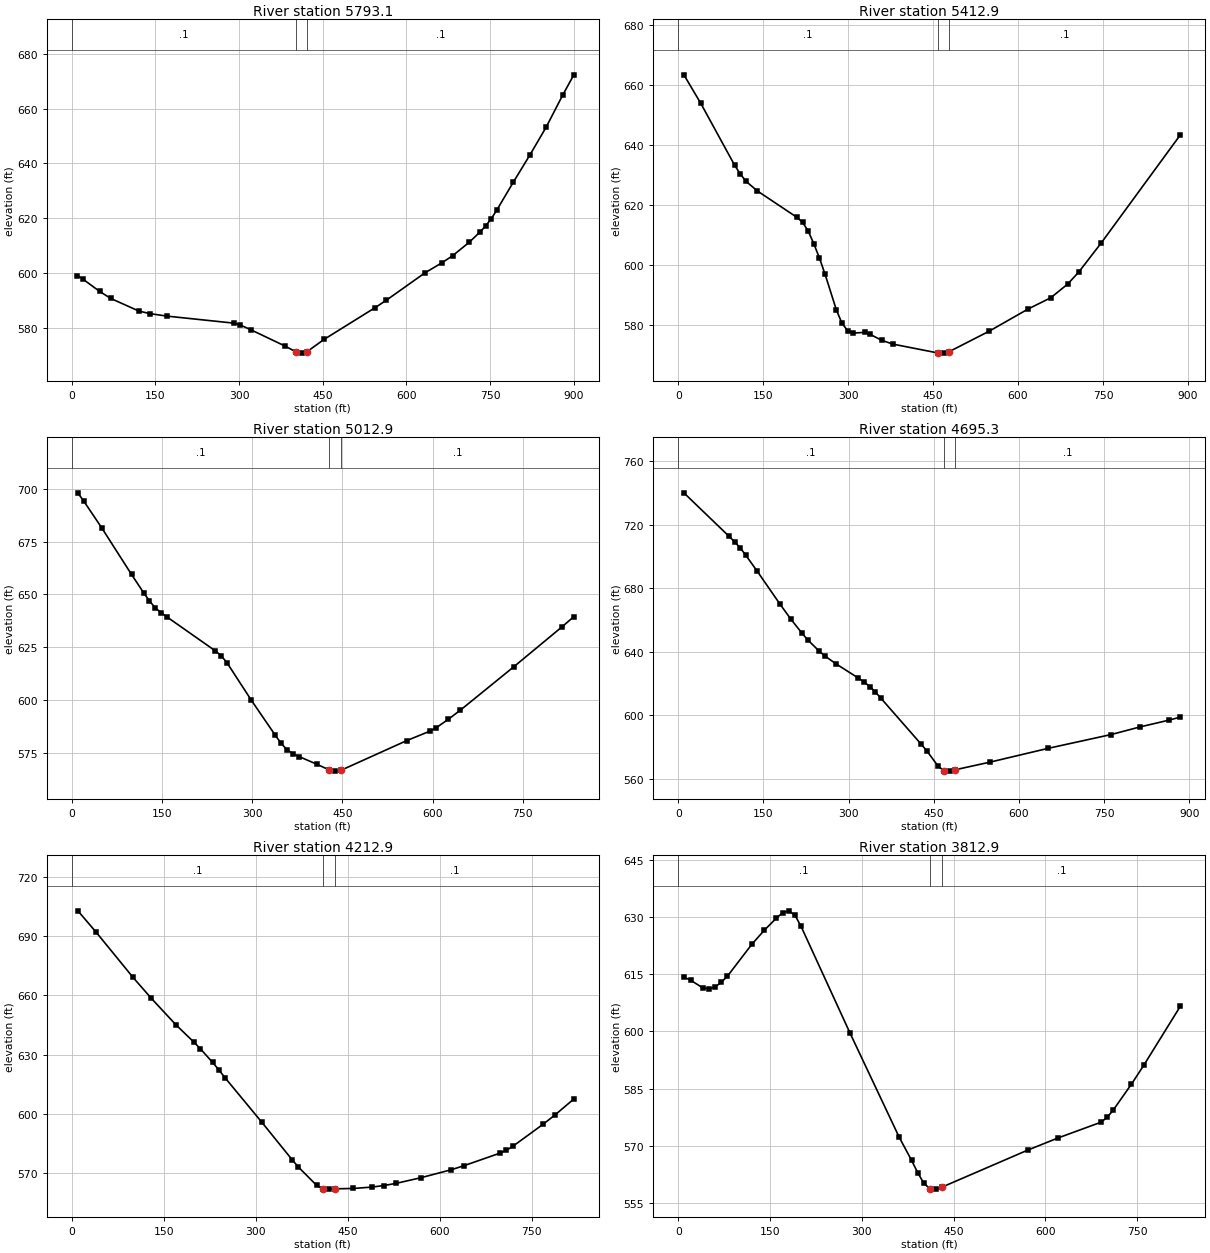
Type RM Length L Ch R = 1 ,5793.1  ,387,380.3,376.2
XS GIS Cut Line= 4
     1545200.112      477459.287     1545431.266      477300.224
      1545712.67      477187.051     1545951.506      476979.791
#Sta/Elev= 30
      10  599.14      20  597.82    50.1  593.32    70.1  590.76   120.3  586.18
   140.3  585.24   170.4  584.34   290.7  581.77   300.8   581.2     321  579.36
   381.7  573.48     402   571.3     412  570.84     422   571.4   452.5  575.87
   543.5  587.38   563.7  590.09   633.3  600.13     663  603.71   682.7  606.34
   712.4  611.25   732.1  615.03     742  617.23   751.9  619.81   761.8  622.94
   791.4  633.12   821.1  643.01   850.7  653.32   880.4  665.04   900.1  672.32
#Mann= 3 , 0 , 0
       0      .1       0     402    .045       0     422      .1       0
Bank Sta=402,422
XS Rating Curve= 0 ,0
Exp/Cntr=0.3,0.1

Type RM Length L Ch R = 1 ,5412.9  ,406.3,400,386.3
XS GIS Cut Line= 3
     1545353.124      477675.431     1545733.019      477400.539
     1546097.001      477195.889
#Sta/Elev= 30
      10  663.33    39.9  653.79    99.8  633.11   109.7  630.24   119.7  627.83
   139.7  624.63   209.5  615.84   219.5  614.19   229.5  611.26   239.4  607.03
   249.4  602.22   259.4  596.79   279.4  584.85   289.3  580.47   299.3     578
   309.3  577.26   329.2  577.48   339.2  576.79   359.2  574.85   379.1  573.57
   458.9  570.61   468.9  570.57   478.9  571.11   548.5  577.83   618.1  585.31
   657.8  589.03   687.6  593.58   707.5  597.67   747.3   607.4   886.5   643.3
#Mann= 3 , 0 , 0
       0      .1       0   458.9    .045       0   478.9      .1       0
Bank Sta=458.9,478.9
XS Rating Curve= 0 ,0
Exp/Cntr=0.3,0.1

Type RM Length L Ch R = 1 ,5012.9  ,315.6,317.6,321.3
XS GIS Cut Line= 3
     1545684.838       477943.97     1545969.701      477612.039
     1546208.185      477294.107
#Sta/Elev= 30
     9.9  698.17    19.9  694.26    49.7  681.62    99.4  659.45   119.3  650.88
   129.2   646.9   139.2  643.53   149.1  641.21   159.1  639.16   238.6  623.26
   248.5  620.93   258.5  617.42   298.2  599.99     338  583.39   347.9  579.45
   357.9  576.34   367.8  574.51   377.8  573.14   407.6  569.47   427.4  566.87
   437.4  566.22   447.4  566.59   556.6  580.65   596.4  585.28   606.3  586.85
   626.2  590.82   646.1  595.12   735.5  615.82     815   634.6   834.8  639.46
#Mann= 3 , 0 , 0
       0      .1       0   427.4    .045       0   447.4      .1       0
Bank Sta=427.4,447.4
XS Rating Curve= 0 ,0
Exp/Cntr=0.3,0.1

Type RM Length L Ch R = 1 ,4695.3  ,476.6,482.4,488.3
XS GIS Cut Line= 3
     1545832.343      478193.758     1546096.159      477910.824
     1546454.983      477566.648
#Sta/Elev= 30
     9.9  739.98    89.3  712.66    99.2  709.17   109.1  705.32     119  700.67
   138.9  690.73   178.5  670.25   198.4  660.42   218.2   651.5   228.1  647.39
     248   640.4   257.9  637.36   277.7  632.35   317.4  623.31   327.3  620.88
   337.3  618.05   347.2  614.57   357.1  610.61   427.4   581.9   437.6  577.61
   457.9  567.78   468.2  565.01   478.2  564.79   488.2  565.68   549.2  570.47
   650.7  579.08   762.3  587.82     813   592.6   863.8  596.86   884.1   598.8
#Mann= 3 , 0 , 0
       0      .1       0   468.2    .045       0   488.2      .1       0
Bank Sta=468.2,488.2
XS Rating Curve= 0 ,0
Exp/Cntr=0.3,0.1

Type RM Length L Ch R = 1 ,4212.9  ,413.4,400,385
XS GIS Cut Line= 3
     1546097.058       478433.17     1546449.571      478224.784
     1546802.084      478016.398
#Sta/Elev= 30
      10  702.95      40  692.01    99.9  669.19   129.8  658.55   169.8  645.16
   199.8  636.17   209.7     633   229.7  626.07   239.7  622.37   249.7  618.39
   309.6  595.87   359.6  576.64   369.5  573.02   399.5  563.67   409.5  561.91
   419.5  561.78   429.5  561.94   459.4  562.12   489.4  562.81   509.4  563.61
   529.4  564.73   569.3  567.55   619.2  571.63   639.2   573.6   699.1   580.1
   709.1  581.51   719.1  583.42   769.1  594.75     789  599.59     819  607.51
#Mann= 3 , 0 , 0
       0      .1       0   409.5    .045       0   429.5      .1       0
Bank Sta=409.5,429.5
XS Rating Curve= 0 ,0
Exp/Cntr=0.3,0.1

Type RM Length L Ch R = 1 ,3812.9  ,411,400,390.9
XS GIS Cut Line= 3
     1546529.271      478856.533     1546728.443      478496.461
     1546901.967      478125.905
#Sta/Elev= 30
      10  614.22    20.1  613.47    40.1  611.46    50.2   611.2    60.2  611.66
    70.3  612.93    80.3   614.5   120.4  622.91   140.5  626.55   160.6  629.79
   170.6  631.18   180.7  631.68   190.7  630.55   200.7  627.62     281  599.51
   361.3   572.2   381.4  566.17   391.4  562.95   401.5  560.14   411.5   558.7
   421.5  558.61   431.5  559.16   571.2  568.85   621.1  572.06   690.9  576.17
   700.9  577.42   710.9  579.33   740.8  586.17   760.8  591.08   820.7  606.61
#Mann= 3 , 0 , 0
       0      .1       0   411.5    .045       0   431.5      .1       0
Bank Sta=411.5,431.5
XS Rating Curve= 0 ,0
Exp/Cntr=0.3,0.1

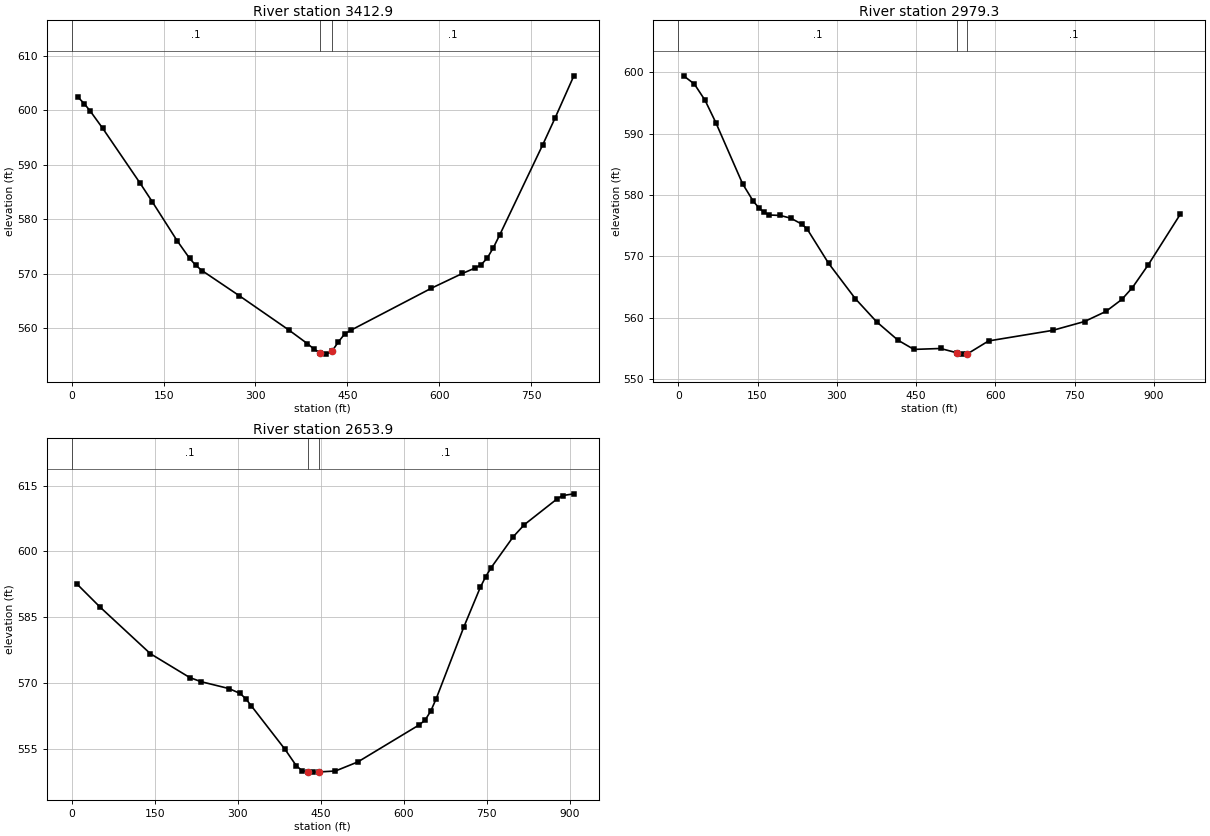
Type RM Length L Ch R = 1 ,3412.9  ,425.7,433.5,449.6
XS GIS Cut Line= 3
     1547044.367      479065.497     1547070.097      478651.016
     1547097.895      478247.285
#Sta/Elev= 30
    10.1  602.44    20.3  601.25    30.4  599.84    50.6   596.7   111.4  586.67
   131.7  583.19   172.2  576.05   192.4  572.84   202.6  571.55   212.7  570.59
   273.5  565.98   354.5  559.68   384.9  557.17     395  556.23   405.3  555.46
   415.3  555.25   425.3  555.84   435.5   557.5   445.6  558.94   455.7  559.63
   587.3  567.35   637.9  570.06   658.1  571.03   668.2  571.63   678.3  572.84
   688.4  574.76   698.6  577.06   769.4  593.74   789.6  598.67     820  606.35
#Mann= 3 , 0 , 0
       0      .1       0   405.3    .045       0   425.3      .1       0
Bank Sta=405.3,425.3
XS Rating Curve= 0 ,0
Exp/Cntr=0.3,0.1

Type RM Length L Ch R = 1 ,2979.3  ,308,325.4,326.9
XS GIS Cut Line= 4
     1547088.634      479094.111     1547296.713      478885.797
     1547625.527      478503.455     1547666.453      478358.207
#Sta/Elev= 30
    10.2  599.45    30.5  598.11    50.8  595.45    71.1  591.82   121.8  581.83
   142.1  578.97   152.3  577.95   162.4  577.16   172.6  576.75   192.9  576.68
   213.2  576.22   233.5  575.27   243.7  574.48   284.3  568.88   334.8  563.12
   375.1  559.34   415.5  556.34   445.7  554.83   496.1  554.98   526.5  554.29
   536.5  554.06   546.5  554.08   586.9  556.21   707.9  557.93   768.5  559.38
   808.8  561.02     839  562.98   859.1  564.92   889.3  568.67   949.6  576.88
#Mann= 3 , 0 , 0
       0      .1       0   526.5    .045       0   546.5      .1       0
Bank Sta=526.5,546.5
XS Rating Curve= 0 ,0
Exp/Cntr=0.3,0.1

Type RM Length L Ch R = 1 ,2653.9  ,2632.1,2653.9,2648.9
XS GIS Cut Line= 4
     1547194.521      479262.864      1547338.77      479054.027
      1547688.36      478870.207     1547894.947       478714.46
#Sta/Elev= 30
    10.2  592.44    50.8  587.32   142.1  576.64   213.2   571.2   233.5  570.26
   284.2  568.68   304.4  567.56   314.6  566.34   324.7  564.71   385.5   554.8
   405.7  551.09   415.9  549.97   426.1  549.65   436.1  549.61   446.1  549.64
   476.6  549.87   517.1  551.94   628.5  560.43   638.7  561.51   648.8  563.52
   658.7  566.37   708.5  582.69   738.3  591.75   748.3  594.26   758.2  596.31
     798  603.34   817.9  606.08   877.7  612.02   887.6  612.74   907.5  613.13
#Mann= 3 , 0 , 0
       0      .1       0   426.1    .045       0   446.1      .1       0
Bank Sta=426.1,446.1
XS Rating Curve= 0 ,0
Exp/Cntr=0.3,0.1

Chan Stop Cuts=-1
Use User Specified Reach Order=0